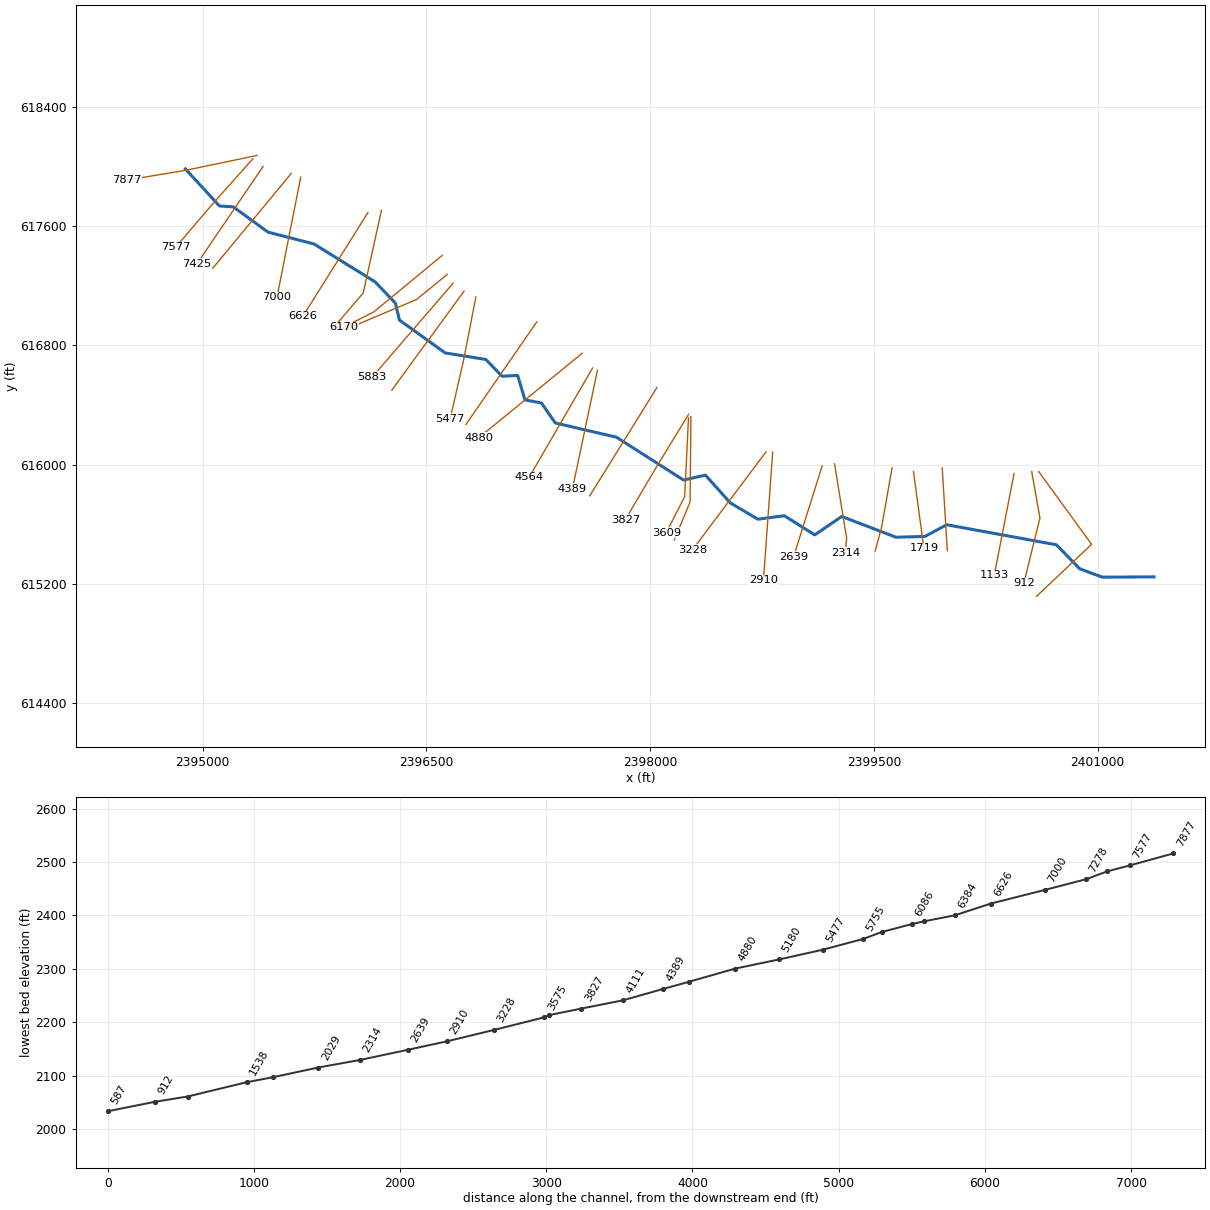
--- REDLCKRN.prj (project) ---

Proj Title=REDLCKRN
Current Plan=p01
Default Exp/Contr=0,0
English Units
Geom File=g01
Flow File=f01
Plan File=p01
BEGIN DESCRIPTION:
Stream Name: Red Lick Run
Flood Zone: Approximate
Pendleton County, West Virginia
HEC-RAS Version: 5.0.7
Hydrology Method:
Regression equation
END DESCRIPTION:
DSS Export Rating Curves= 0
DSS Export Rating Curve Sorted= 0
DSS Export Volume Flow Curves= 0
DXF OffsetX= 0
DXF OffsetY= 0
DXF ScaleX= 0
DXF ScaleY= 0

--- REDLCKRN.p01 (plan) ---

Plan Title=Floodplain
Program Version=5.07
Short Identifier=Floodplain
Geom File=g01
Flow File=f01
Subcritical Flow
K Sum by GR= 0
Std Step Tol= 0.01
Critical Tol= 0.01
Num of Std Step Trials= 20
Max Error Tol= 0.3
Flow Tol Ratio= 0.001
Split Flow NTrial= 30
Split Flow Tol= 0.02
Split Flow Ratio= 0.02
Log Output Level= 0
Friction Slope Method= 1
Unsteady Friction Slope Method= 2
Unsteady Bridges Friction Slope Method= 1
Parabolic Critical Depth
Global Vel Dist= 0 , 0 , 0
Global Log Level= 0
CheckData=False
Encroach Param=-1 ,0,0, 0
Mapping Interval=1HOUR
Computation Time Step Use Courant=        0
Computation Time Step Use Time Series=    0
Computation Time Step Count To Double=0
Computation Time Step Max Doubling=0
Computation Time Step Max Halving=0
Computation Time Step Residence Courant=0
Run HTab= 0
Run UNet= 0
Run Sediment= 0
Run PostProcess= 0
Run WQNet= 0
Run RASMapper= 0
UNET Theta= 0
UNET Theta Warmup= 0
UNET ZTol= 0
UNET ZSATol= 0
UNET MxIter= 0
UNET Max Iter WO Improvement= 0
UNET MaxInSteps= 0
UNET DtIC= 0
UNET DtMin= 0
UNET MaxCRTS= 0
UNET WFStab= 0
UNET SFStab= 0
UNET WFX= 1
UNET SFX= 1
UNET 1D Methodology=Finite Difference
UNET DSS MLevel= 1
UNET Pardiso=0
UNET DZMax Abort= 0
UNET Use Existing IB Tables= 0
UNET Froude Reduction=False
UNET Froude Limit= 0
UNET Froude Power= 0
UNET D1 Cores= 0
UNET D2 Coriolis=0
UNET D2 Cores= 0
UNET D2 Theta= 1
UNET D2 Theta Warmup= 1
UNET D2 Z Tol= 0.01
UNET D2 Volume Tol= 0.01
UNET D2 Max Iterations= 20
UNET D2 Equation= 0
UNET D2 RampUpFraction=0.1
UNET D2 TimeSlices= 1
UNET D2 BCVolumeCheck=0
UNET D1D2 MaxIter= 0
UNET D1D2 ZTol=0.01
UNET D1D2 QTol=0.1
UNET D1D2 MinQTol=1
Write IC File= 0
Write IC File at Fixed DateTime=0
Write IC File at Sim End=0
Echo Input=False
Echo Parameters=False
Echo Output=False
Write Detailed= 0
HDF Write Warmup=0
HDF Write Time Slices=0
HDF Flush=0
HDF Face Node Velocities=0
HDF Compression= 1
HDF Chunk Size= 1
HDF Spatial Parts= 1
HDF Use Max Rows=0
HDF Fixed Rows= 1
Calibration Method= 0
Calibration Iterations= 20
Calibration Max Change=0.05
Calibration Tolerance=0.2
Calibration Maximum=1.5
Calibration Minimum=0.5
Calibration Optimization Method= 1
WQ AD Non Conservative
WQ ULTIMATE=-1
WQ Max Comp Step=1HOUR
WQ Output Interval=15MIN
WQ Output Selected Increments= 0
WQ Output face flow=0
WQ Output face velocity=0
WQ Output face area=0
WQ Output face dispersion=0
WQ Output cell volume=0
WQ Output cell surface area=0
WQ Output cell continuity=0
WQ Output cumulative cell continuity=0
WQ Output face conc=0
WQ Output face dconc_dx=0
WQ Output face courant=0
WQ Output face peclet=0
WQ Output face adv mass=0
WQ Output face disp mass=0
WQ Output cell mass=0
WQ Output cell source sink temp=0
WQ Output nsm pathways=0
WQ Output nsm derived pathways=0
WQ Output MaxMinRange=-1
WQ Daily Max Min Mean=-1
WQ Daily Range=0
WQ Daily Time=0
WQ Create Restart=0
WQ Fixed Restart=0
WQ System Summary=0
WQ Write To DSS=0
WQ Use Fixed Temperature=0
Sorting and Armoring Iterations= 10
XS Update Threshold= 0.02
Bed Roughness Predictor= 0
Hydraulics Update Threshold= 0.02
Energy Slope Method= 1
Volume Change Method= 1
Sediment Retention Method= 0
XS Weighting Method= 0
Number of US Weighted Cross Sections= 1
Number of DS Weighted Cross Sections= 1
Upstream XS Weight=0
Main XS Weight=1
Downstream XS Weight=0
Number of DS XS's Weighted with US Boundary= 1
Upstream Boundary Weight= 1
Weight of XSs Associated with US Boundary= 0
Number of US XS's Weighted with DS Boundary= 1
Downstream Boundary Weight= 0.5
Weight of XSs Associated with DS Boundary= 0.5
Percentile Method= 0
Sediment Output Level= 3
Mass or Volume Output= 0
Output Increment Type= 1
Profile and TS Output Increment= 1
XS Output Flag= 0
XS Output Increment= 10
Write Gradation File= 0
Read Gradation Hotstart= 0
Write HDF5 File= 1
Write Binary Output= 1
Write DSS Sediment File= 0
SV Curve= 0
Specific Gage Flag= 0

--- REDLCKRN.f01 (steady flow) ---

Flow Title=Flows
Program Version=5.07
Number of Profiles= 6
Profile Names=P100yr,P10yr,P25yr,P50yr,P500yr,P101yr
River Rch & RM=REDLCKRN,Main            ,7877
     543     254     359     448     795     660
River Rch & RM=REDLCKRN,Main            ,6626
     620     290     410     512     909     754
Boundary for River Rch & Prof#=REDLCKRN,Main            , 1
Up Type= 0
Dn Type= 3
Dn Slope=0.02358
Boundary for River Rch & Prof#=REDLCKRN,Main            , 2
Up Type= 0
Dn Type= 3
Dn Slope=0.02358
Boundary for River Rch & Prof#=REDLCKRN,Main            , 3
Up Type= 0
Dn Type= 3
Dn Slope=0.02358
Boundary for River Rch & Prof#=REDLCKRN,Main            , 4
Up Type= 0
Dn Type= 3
Dn Slope=0.02358
Boundary for River Rch & Prof#=REDLCKRN,Main            , 5
Up Type= 0
Dn Type= 3
Dn Slope=0.02358
Boundary for River Rch & Prof#=REDLCKRN,Main            , 6
Up Type= 0
Dn Type= 3
Dn Slope=0.02358
DSS Import GetInterval= 0
DSS Import GetPeak= 0
DSS Import FillOption= 0

--- REDLCKRN.g01 (geometry) ---

Geom Title=Geometry
Program Version=5.07

River Reach=REDLCKRN        ,Main
Reach XY= 30
2394883.30000001617983.4839999972395112.23700002 617734.67400001
     2395205.039 617728.64200002     2395438.396617559.072000012
2395746.06200004617480.101000011     2396155.081617226.462000012
2396291.83600003617083.3820000142396318.94700003616969.605000019
2396625.71100003616749.5500000122396898.12700003616705.670000002
2397007.02700001616592.961999998     2397111.419616598.525000021
2397160.67500004616434.4360000042397271.14500004616413.765000001
2397363.79500002616279.8490000222397774.14200002616184.249000013
2398223.85800001615897.0289999992398370.70302951615930.147237316
     2398537.447615743.7430000012398722.50900003615634.465000018
2398899.83800003615657.7919999962399103.54200003      615529.287
2399284.25299999615652.780000001     2399648.521615513.655000001
     2399842.542615519.225000009     2399988.632 615597.38000001
2400723.72400001615463.0730000142400879.53100002615302.673000008
2401031.74400002615245.8910000032401378.66510615615247.921737805

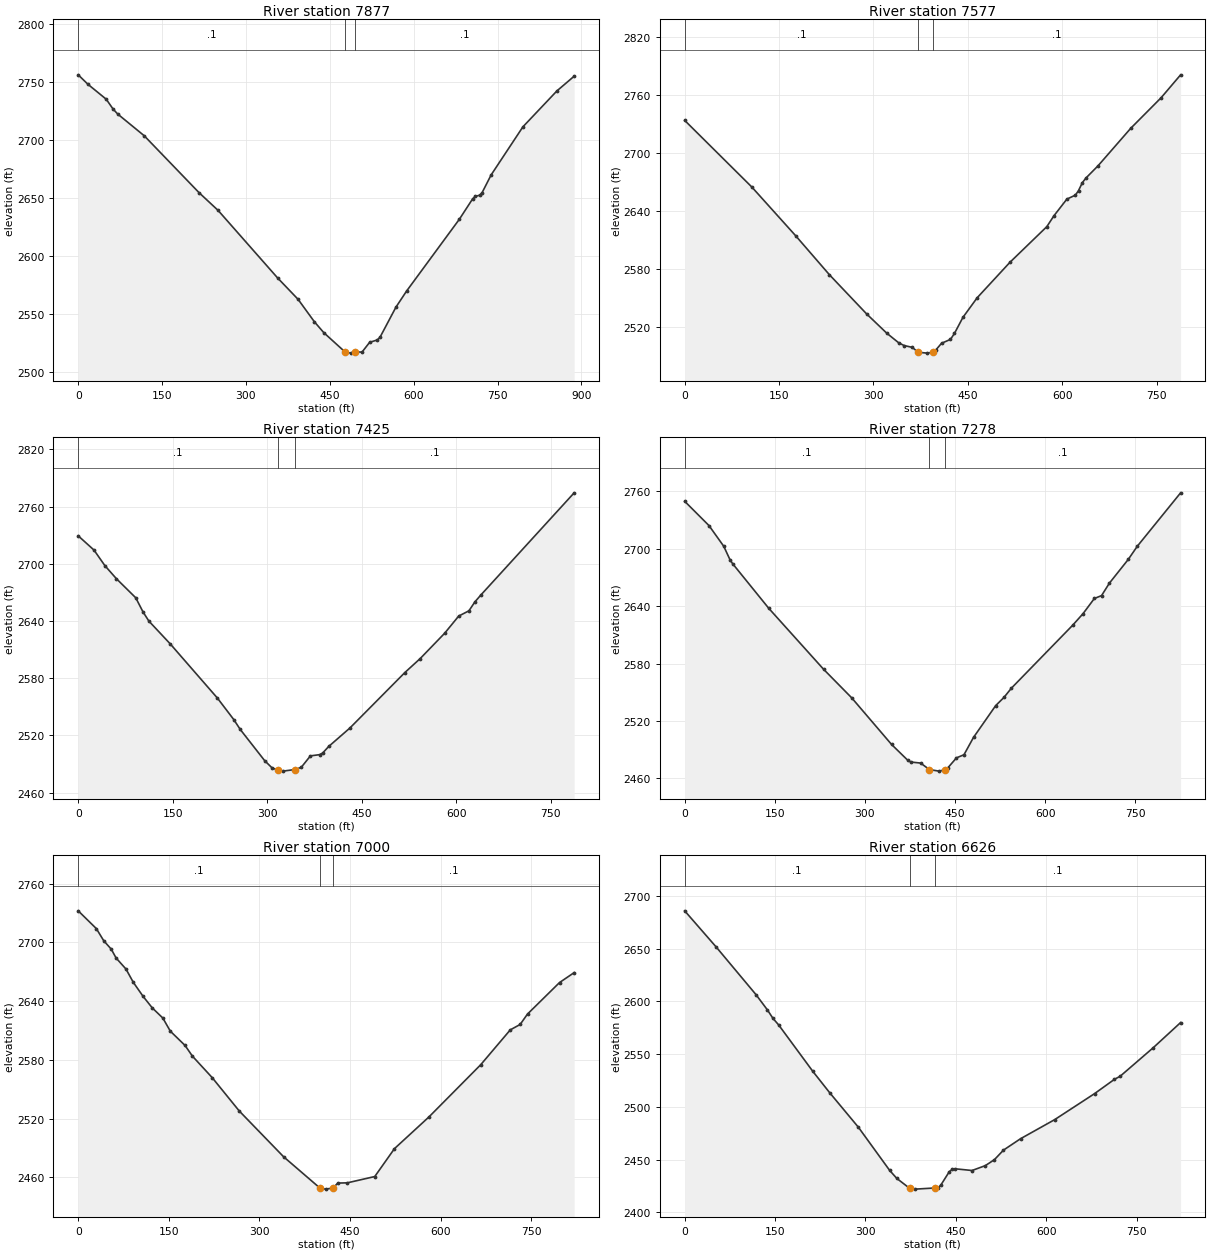
Type RM Length L Ch R = 1 ,7877    ,287.4,300,303.3
XS GIS Cut Line= 3
2395363.74431623 618073.42857044     2394884.003      617973.531
     2394492.388      617908.668
#Sta/Elev= 30
       0 2756.36    17.4 2748.19    50.1  2735.3    62.3 2726.86    70.6 2722.52
     118 2703.78     216 2654.68   250.3 2639.26   356.5 2581.06   393.3 2562.51
   422.3 2543.22   439.2 2533.77   476.4 2517.46   487.2 2516.08   495.4  2517.3
   507.5  2516.9   521.2  2525.4   535.2 2527.51     540 2529.99   568.3  2555.8
   587.3 2569.67   681.9 2631.81   705.6  2649.4   710.2 2651.35   718.4  2652.5
   722.4 2654.67   738.6 2670.01   795.4 2711.49   856.2 2742.49     887 2755.16
#Mann= 3 ,-1 , 0
       0      .1       0   476.4    .045       0   495.4      .1       0
Bank Sta=476.4,495.4
XS Rating Curve= 0 ,0
Exp/Cntr=0.3,0.1

Type RM Length L Ch R = 1 ,7577    ,150.7,152.6,152.6
XS GIS Cut Line= 3
2395335.56581157618050.474322767     2395078.742      617762.802
      2394817.45      617456.409
#Sta/Elev= 30
       0 2734.14   106.7 2665.25   176.4 2614.85     230 2574.56   289.2    2534
   321.2 2514.08   340.2 2504.12   348.7  2501.3   361.6 2499.43   371.4 2494.32
   385.5 2493.44   394.1 2494.37   399.8 2497.15   408.3 2503.63   422.5 2507.66
   428.8  2513.8   442.3 2530.45     465 2550.76   516.9  2587.3   575.7  2624.3
     587 2635.55   607.5 2652.73   621.1 2656.85     626 2661.52   632.2 2669.86
   638.1 2674.72   656.9 2687.07     709 2725.95   757.3 2757.57   788.3 2781.26
#Mann= 3 ,-1 , 0
       0      .1       0   371.4    .045       0   394.1      .1       0
Bank Sta=371.4,394.1
XS Rating Curve= 0 ,0
Exp/Cntr=0.3,0.1

Type RM Length L Ch R = 1 ,7425    ,150.1,147.1,145.6
XS GIS Cut Line= 2
 2395404.8127812617999.634471818 2394962.4553165617348.754278527
#Sta/Elev= 30
       0 2729.27    25.1  2714.3    42.3 2698.03    60.6 2684.31    91.3  2664.3
   102.8 2649.52   112.1 2639.89     146 2615.97   220.9  2559.1   246.8 2536.61
   257.2 2526.16   295.9 2493.46   307.2 2486.15   316.8 2483.43   324.9  2482.5
   344.3  2484.2     354 2486.52   368.5 2498.49     383 2499.77   387.9 2501.46
   397.5 2508.37   431.1 2527.69   518.4 2585.92   542.6 2600.49   581.3 2626.96
   603.8 2645.12     620 2650.62   629.6 2660.09   639.3 2667.46     787 2774.37
#Mann= 3 ,-1 , 0
       0      .1       0   316.8    .045       0   344.3      .1       0
Bank Sta=316.8,344.3
XS Rating Curve= 0 ,0
Exp/Cntr(USF)=0,0
Exp/Cntr=0.3,0.1

Type RM Length L Ch R = 1 ,7278    ,272.7,277.6,282
XS GIS Cut Line= 2
2395593.61472201617952.998075094 2395067.1989473617317.118669308
#Sta/Elev= 30
       0 2749.56    40.5 2724.14      65 2702.59    75.4 2688.54    79.8 2684.37
   139.9 2637.76   231.2 2574.02     278 2544.17   344.4 2495.41   371.4 2478.88
   376.6 2477.05   392.7    2476   407.52469.153   423.4 2467.57   432.5 2468.87
   438.2 2471.13   452.4 2481.44   464.9  2484.7   480.8 2502.85   517.7 2536.05
   531.4 2544.57   543.9  2554.3   645.6 2619.88   663.1 2632.15   681.9 2647.97
   693.9 2651.01     707 2664.05   738.4 2688.85   753.5 2702.66   825.5  2758.4
#Mann= 3 ,-1 , 0
       0      .1       0   407.5    .045       0   432.5      .1       0
Bank Sta=407.5,432.5
XS Rating Curve= 0 ,0
Exp/Cntr=0.3,0.1

Type RM Length L Ch R = 1 ,7000    ,376.4,373.9,380.5
XS GIS Cut Line= 2
     2395657.207      617928.366     2395497.856      617123.213
#Sta/Elev= 30
       0 2732.36      30  2714.2    42.3 2701.72    54.7 2693.17    62.7 2684.12
      79 2672.89    91.2 2659.23   107.5  2644.8   122.5 2633.16   140.1 2622.71
   152.4 2609.35   176.8 2594.74   189.1 2583.73   221.7 2561.85   266.5 2527.73
   339.9 2480.92   400.4 2448.74   409.3 2447.82   421.5 2448.93   429.7 2454.02
   445.3 2454.24   490.8 2460.69   523.4 2489.21   580.5 2521.64   666.2 2575.04
   715.1 2610.65   731.4 2616.17   743.6 2626.83   796.6 2659.03   820.8 2669.18
#Mann= 3 ,-1 , 0
       0      .1       0   400.4    .045       0   421.5      .1       0
Bank Sta=400.4,421.5
XS Rating Curve= 0 ,0
Exp/Cntr=0.3,0.1

Type RM Length L Ch R = 1 ,6626    ,237.6,242.7,246.4
XS GIS Cut Line= 2
2396107.99475108617691.0681330352395670.50575108616993.909133035
#Sta/Elev= 30
       0 2685.72    52.2  2651.5   118.3 2606.35   137.2 2591.91   146.6 2583.73
     156 2577.57   212.7 2533.56     241  2513.1   288.3 2480.63   340.2 2439.72
   352.1 2432.11   373.3 2422.77   382.7 2421.97   416.2 2423.09   420.5 2423.46
   424.7 2425.42   439.2 2438.53   444.1 2440.68   448.8 2441.25   476.9 2439.62
     499 2444.24   514.1 2449.91   529.1 2458.94   557.4 2469.73   614.1 2487.84
   680.2 2512.45   713.3 2526.04   722.7 2528.91   777.5 2555.91   823.1 2579.84
#Mann= 3 ,-1 , 0
       0      .1       0   373.3    .045       0   416.2      .1       0
Bank Sta=373.3,416.2
XS Rating Curve= 0 ,0
Exp/Cntr=0.3,0.1

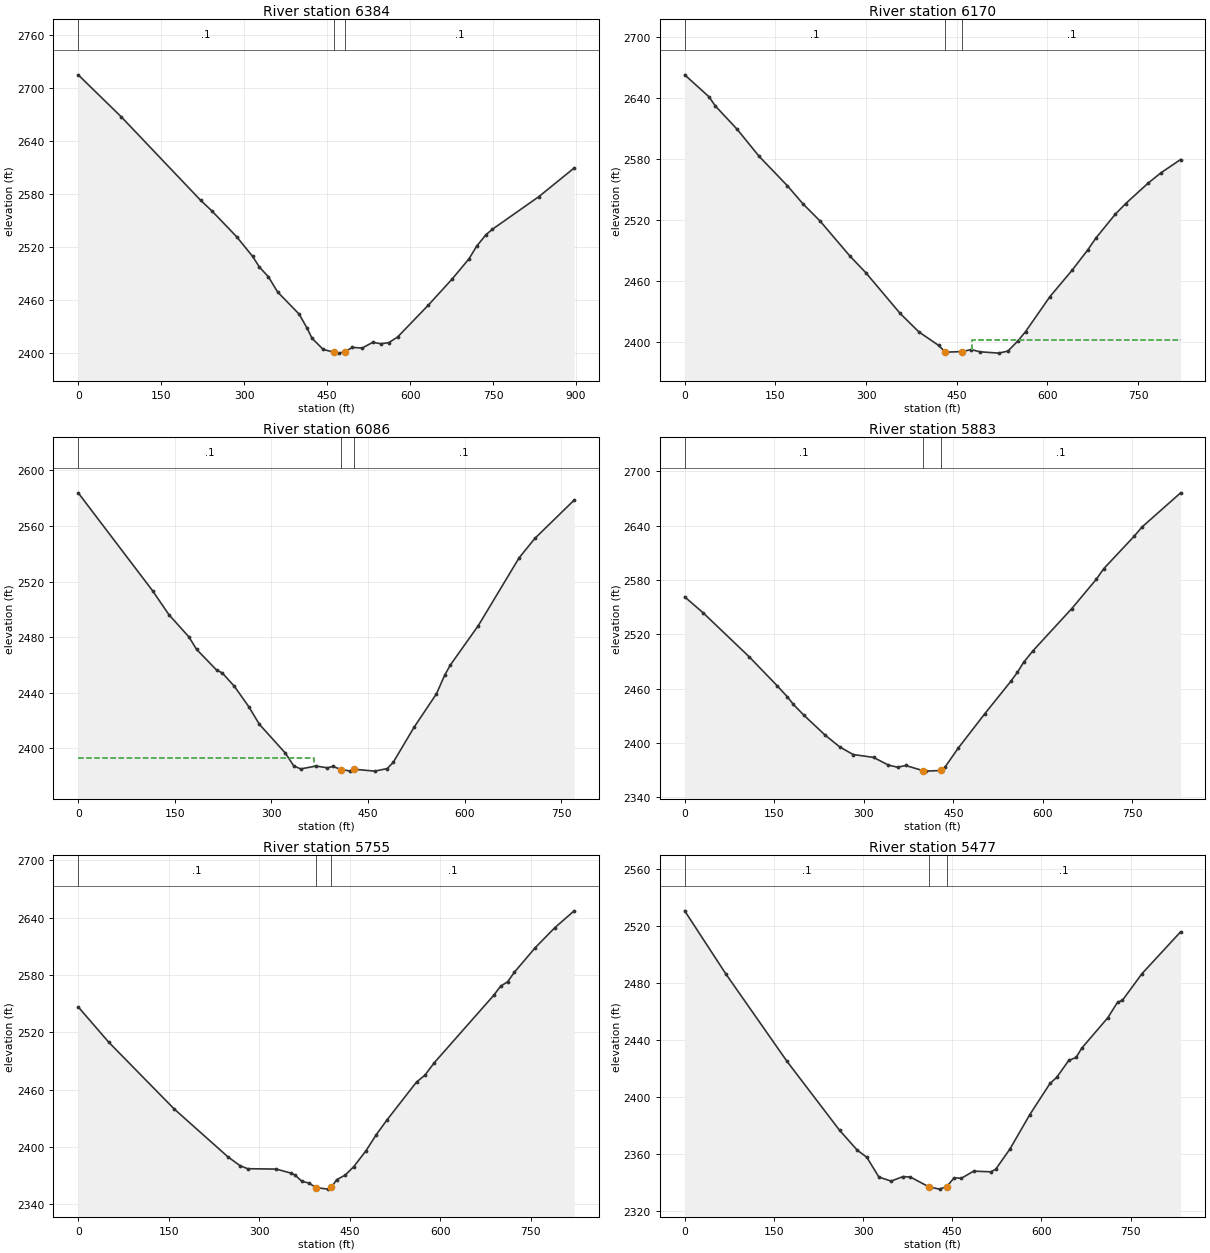
Type RM Length L Ch R = 1 ,6384    ,221.9,214,207.7
XS GIS Cut Line= 3
2396198.57105673617706.8282428592396076.16092714617151.183032447
     2395862.834      616902.546
#Sta/Elev= 30
       0 2715.43    77.8 2667.88   221.1 2573.45   241.5 2561.39   286.7 2531.85
   315.3 2509.77   327.6 2497.66     344 2486.54   360.4 2469.51   399.4 2444.36
   413.6 2428.64   422.7 2417.07   442.9 2404.32   462.4 2401.24     471 2400.18
   482.6 2401.84   495.5 2406.65   513.3 2405.94   532.4 2412.35   546.9 2410.88
   561.1 2411.96   577.3 2418.36   632.6  2454.3   675.6 2483.83   706.4 2506.92
   720.5 2521.49   737.5 2534.52   748.9 2540.53   832.9 2577.51   896.6 2609.88
#Mann= 3 ,-1 , 0
       0      .1       0   462.4    .045       0   482.6      .1       0
Bank Sta=462.4,482.6
XS Rating Curve= 0 ,0
Exp/Cntr=0.3,0.1

Type RM Length L Ch R = 1 ,6170    ,87.2,83,80.9
XS GIS Cut Line= 3
2396605.68702044617403.2311578232396146.65331565617024.290449119
2395945.72091914616922.789854352
#Sta/Elev= 30
       0 2662.92    40.1 2641.36    50.6 2632.34    86.8 2609.27   123.1 2582.65
     170 2553.59   195.7  2535.8     224 2518.87   273.5 2484.27   299.5 2468.06
   356.5  2427.8   387.6 2409.54     420  2396.4   431.4 2389.69   459.2 2390.24
     474 2392.26   488.2 2390.07   519.5 2388.73   534.6 2390.73   550.7 2400.42
     564    2410   604.1  2444.3   640.9 2470.42   666.8 2490.44   680.3 2502.14
   712.3 2525.58   729.6 2536.12   766.9 2556.35   787.8 2566.34   820.4 2579.49
#Mann= 3 ,-1 , 0
       0      .1       0   431.4    .045       0   459.2      .1       0
#XS Ineff= 2 , 0
                          474.56         2401.88
Permanent Ineff=
       F       F
Bank Sta=431.4,459.2
XS Rating Curve= 0 ,0
Exp/Cntr=0.3,0.1

Type RM Length L Ch R = 1 ,6086    ,199.1,203.7,206.5
XS GIS Cut Line= 3
2396639.95300275617276.1649221512396432.49249413617106.924114862
2395969.34506629616912.300233286
#Sta/Elev= 30
       0 2583.89   115.5  2513.4   140.9 2496.17   171.9 2480.19   183.7 2471.29
     215 2456.28   223.5 2454.36   242.5 2444.63   264.8 2430.02   281.3 2417.33
   321.7 2396.56   334.7 2387.36   345.5  2385.2   369.4 2387.26   386.8 2385.99
   395.5 2386.99   408.5 2384.69   421.5 2383.77     428 2384.99   460.5  2383.6
   479.9 2385.45   489.1  2389.9   521.3    2415   556.3 2439.27     569 2452.57
   577.7 2459.89   621.1 2488.21   684.6 2537.09     709 2551.05   770.1 2578.66
#Mann= 3 ,-1 , 0
       0      .1       0   408.5    .045       0     428      .1       0
#XS Ineff= 2 , 0
           366.9 2393.06
Permanent Ineff=
       F       F
Bank Sta=408.5,428
XS Rating Curve= 0 ,0
Exp/Cntr=0.3,0.1

Type RM Length L Ch R = 1 ,5883    ,125.4,127.7,128.3
XS GIS Cut Line= 2
2396678.99139358617216.907562718 2396136.5912325 616587.72337587
#Sta/Elev= 30
       0 2561.39      31 2543.69   108.3 2494.99   154.8 2463.24   171.7 2451.17
   182.2 2442.44   200.1 2430.36     235 2408.78   259.7 2395.57   282.2 2387.19
   316.4    2384   340.7 2375.66   356.5 2373.14   370.3 2375.05   398.6 2369.46
     404 2368.83   429.2 2369.56   435.7 2372.97   458.2 2394.27   502.7 2432.24
   546.2 2467.98   557.2 2477.93   567.7 2488.97     583 2501.53   648.3 2548.33
   689.2  2580.6   702.1  2592.6   753.2 2628.55   766.1 2638.57   830.7 2676.29
#Mann= 3 ,-1 , 0
       0      .1       0   398.6    .045       0   429.2      .1       0
Bank Sta=398.6,429.2
XS Rating Curve= 0 ,0
Exp/Cntr(USF)=0,0
Exp/Cntr=0.3,0.1

Type RM Length L Ch R = 1 ,5755    ,271.4,277.6,281.4
XS GIS Cut Line= 2
      2396752.29       617163.78     2396267.725      616499.833
#Sta/Elev= 30
       0 2546.55    50.6 2509.56   159.2 2439.65   247.9 2389.76     268 2380.47
   280.8  2377.2   328.3 2376.81   352.7 2372.58   359.6 2370.46     371 2363.86
   382.4 2362.28   393.9 2357.44     414 2355.83   419.7 2357.72   428.3 2365.68
   442.6 2370.54   456.7 2379.37     477 2395.99   494.1 2412.88   511.5    2428
   560.7  2467.9   574.3 2474.82   590.4 2488.27   688.8 2558.73   700.2 2568.25
   711.7 2572.79   723.1 2582.92   757.5 2608.49   789.7 2629.23     822 2647.05
#Mann= 3 ,-1 , 0
       0      .1       0   393.9    .045       0   419.7      .1       0
Bank Sta=393.9,419.7
XS Rating Curve= 0 ,0
Exp/Cntr=0.3,0.1

Type RM Length L Ch R = 1 ,5477    ,295.3,297.4,291.5
XS GIS Cut Line= 3
     2396831.204       617123.76      2396749.67      616703.261
     2396658.993      616307.522
#Sta/Elev= 30
       0 2530.81    69.4 2486.47     172  2425.3   260.5  2376.9   290.2 2362.96
   306.5 2357.87   326.8 2343.98   347.2 2341.24   367.6  2344.4   379.8 2344.04
   410.7 2337.21   428.7 2335.58   440.9 2337.37   453.3  2343.5   465.6 2343.24
   486.2  2348.2   514.9 2347.73   523.1 2349.45   547.4 2363.87   580.5  2387.8
   614.7 2409.79   625.7 2413.91   646.2  2425.9   658.5 2427.96   668.1 2434.55
   711.9 2455.86   728.2 2466.66   736.5  2468.1   769.3 2486.73   834.3  2516.1
#Mann= 3 ,-1 , 0
       0      .1       0   410.7    .045       0   440.9      .1       0
Bank Sta=410.7,440.9
XS Rating Curve= 0 ,0
Exp/Cntr=0.3,0.1

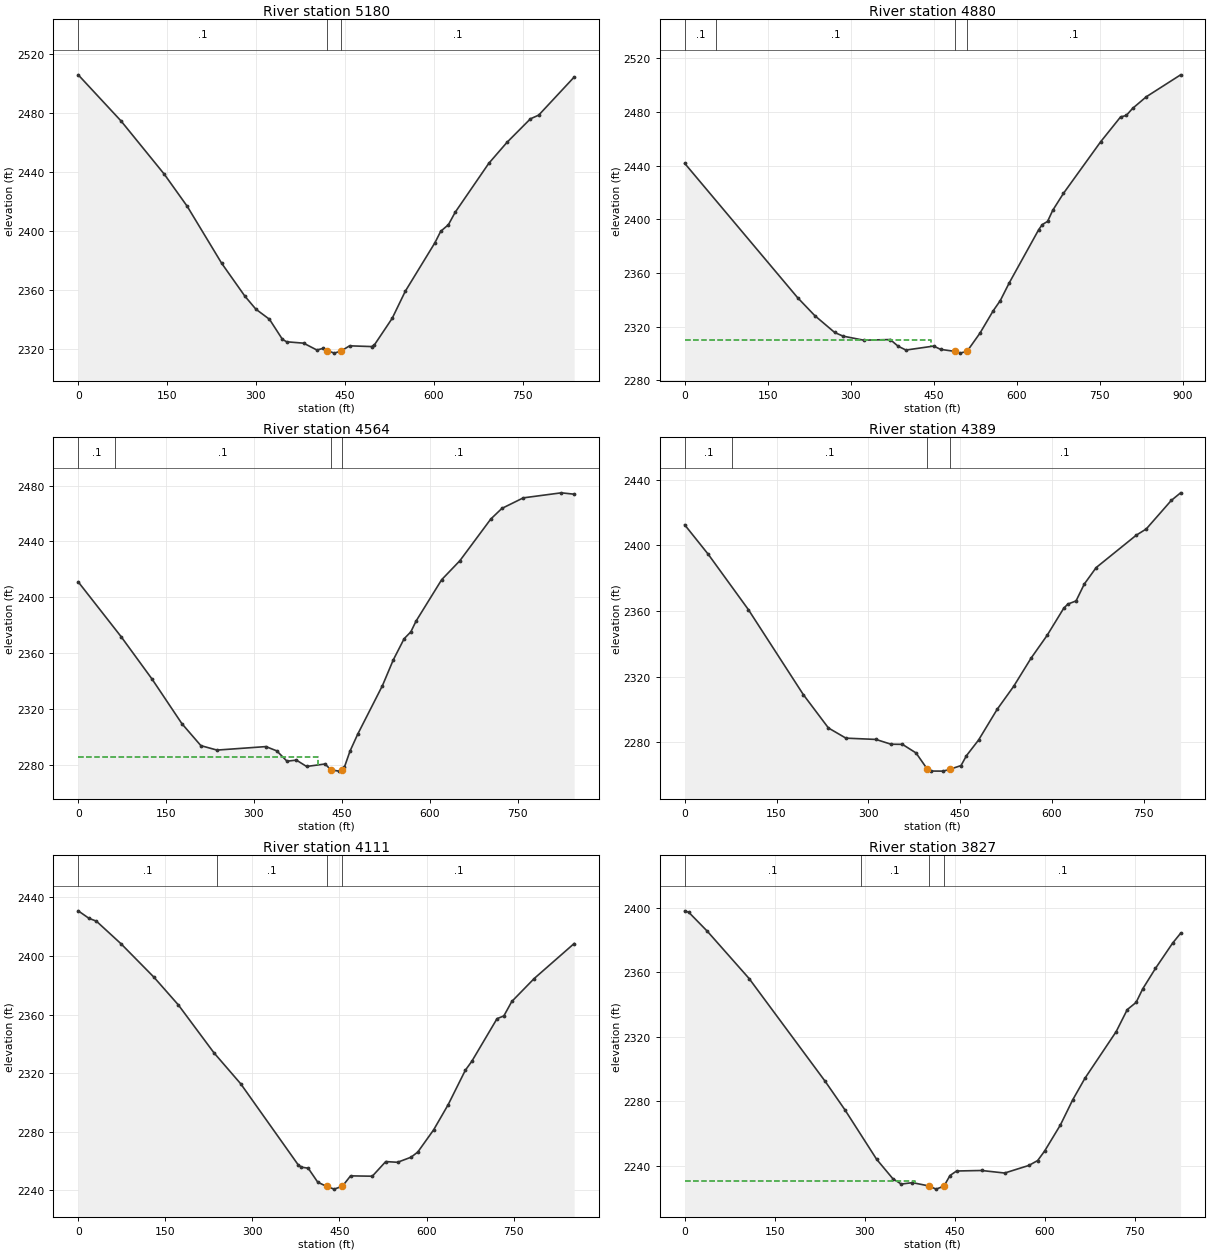
Type RM Length L Ch R = 1 ,5180    ,301.4,299.9,295
XS GIS Cut Line= 2
2397240.37669942616958.366503401     2396764.792      616269.576
#Sta/Elev= 30
       0 2505.71    72.3 2474.49   145.2 2438.52   184.1 2416.68   242.2 2378.16
   281.3 2355.97   299.8 2347.18   322.8 2340.32   344.5 2326.86   351.6 2325.11
   380.4 2324.17   402.8 2319.54   412.5 2320.57   420.6 2319.15   432.1 2317.43
   443.6 2318.86     458 2322.37   495.2 2321.87     500 2323.07   529.9 2340.98
     552 2359.29   602.1 2392.15   611.8 2399.86   624.8 2404.31   636.1 2412.65
   692.8 2445.76   723.6 2460.01   763.2 2475.95   777.2 2478.45     837 2504.18
#Mann= 3 ,-1 , 0
       0      .1       0   420.6    .045       0   443.6      .1       0
Bank Sta=420.6,443.6
XS Rating Curve= 0 ,0
Exp/Cntr=0.3,0.1

Type RM Length L Ch R = 1 ,4880    ,311.4,316.1,317.6
XS GIS Cut Line= 2
2397544.66175536616747.439685311     2396850.734      616180.832
#Sta/Elev= 30
       0 2441.83   203.9 2341.72   234.9 2328.35     271 2315.72     286 2313.01
   323.4 2309.98   371.3 2310.45   385.5 2305.51   399.7 2302.62   449.9 2305.59
   462.3 2303.12   487.9 2301.66   487.9 2301.65   498.2 2300.33   510.6 2301.96
   533.4 2315.22   557.4 2331.95   570.1 2339.47     586 2352.47   639.6 2392.43
     646 2396.15   655.6 2398.56   664.9 2406.81   684.1 2419.35   751.3 2457.82
   787.4 2476.41   797.7  2477.5   809.1 2482.76   833.9 2491.45   895.9 2507.81
#Mann= 4 ,-1 , 0
       0      .1       0   56.93      .1       0   487.9    .045       0
   510.6      .1       0
#XS Ineff= 2 , 0
          444.87 2309.96
Permanent Ineff=
       F       F
Bank Sta=487.9,510.6
XS Rating Curve= 0 ,0
Exp/Cntr=0.3,0.1

Type RM Length L Ch R = 1 ,4564    ,171.1,175,177.3
XS GIS Cut Line= 2
     2397613.625      616648.029     2397188.809      615915.834
#Sta/Elev= 30
       0 2411.07    73.2 2371.86   126.2 2341.39     177 2309.57   209.4 2293.84
   236.9 2290.67   320.4 2293.17   338.9 2290.11   356.4 2282.72   372.4 2283.49
   389.8 2278.94   421.4 2280.72   431.4 2276.46   445.3 2275.61   450.92276.527
   454.5 2278.61   463.8 2289.82     477 2301.99   519.3 2336.83   537.8 2355.24
   556.3 2370.38   567.8 2375.32   576.5 2382.88   620.4 2412.64   651.4 2426.18
   704.2 2456.03   723.1 2463.62   759.7 2471.19   824.5 2474.79   846.5 2473.81
#Mann= 4 ,-1 , 0
       0      .1       0   62.86      .1       0   431.4    .045       0
   450.9      .1       0
#XS Ineff= 2 , 0
          408.59 2285.63
Permanent Ineff=
       F       F
Bank Sta=431.4,450.9
XS Rating Curve= 0 ,0
Exp/Cntr=0.3,0.1

Type RM Length L Ch R = 1 ,4389    ,280.9,278.5,274.8
XS GIS Cut Line= 2
2397646.48742656616632.6076853112397479.24555253615839.963314689
#Sta/Elev= 30
       0 2412.53    38.5 2394.55     104 2360.84   193.9 2308.93   234.8 2288.64
   263.4 2282.43   312.4 2281.65     337 2278.73   355.7 2278.65   377.9 2273.41
   396.3 2263.57     403 2262.37   422.2 2262.32   432.6 2263.38   451.4 2265.71
   460.3 2271.76   480.1 2281.31   510.3 2299.94   537.3 2313.97   565.9 2331.26
     592 2345.09   619.1  2361.6   625.8 2364.17   639.3 2366.11   652.8 2376.43
   672.2 2386.46   737.6 2406.18     754    2410   794.8 2427.38   810.1 2432.03
#Mann= 4 ,-1 , 0
       0      .1       0   77.17      .1       0   396.3    .045       0
   432.6      .1       0
Bank Sta=396.3,432.6
XS Rating Curve= 0 ,0
Exp/Cntr=0.3,0.1

Type RM Length L Ch R = 1 ,4111    ,285.8,283.1,284.7
XS GIS Cut Line= 2
2398045.47918871 616517.51884631     2397595.167      615791.652
#Sta/Elev= 30
       0 2430.81    18.4 2425.72    31.3 2423.75    73.7 2408.32   130.2 2385.59
   172.4  2366.6   233.7 2333.91   279.9 2312.69   378.6 2257.51   384.4 2255.76
   396.1 2255.07   412.6  2245.5     428 2242.58   440.9 2240.76     455 2242.73
   469.1 2249.82   506.5 2249.58   529.7 2259.58     550 2259.09   573.3 2262.56
   584.9  2266.1   612.2 2281.26   637.2 2298.43   666.8 2321.97   677.9 2328.04
   721.4 2357.18   733.1 2359.03   746.8  2368.9   785.3 2384.55   854.2 2408.48
#Mann= 4 ,-1 , 0
       0      .1       0  238.61      .1       0     428    .045       0
     455      .1       0
Bank Sta=428,455
XS Rating Curve= 0 ,0
Exp/Cntr=0.3,0.1

Type RM Length L Ch R = 1 ,3827    ,211.9,218.3,225.6
XS GIS Cut Line= 3
     2398258.327      616338.904     2398040.502      615982.018
     2397833.045       615630.36
#Sta/Elev= 30
       0 2398.24     6.9  2397.3    37.5 2385.65   107.4 2356.18   234.3 2292.26
   267.1 2274.62   319.8 2243.98   346.8 2231.93   360.9 2228.56   379.6 2229.44
   407.7 2227.34   418.8 2225.42     4322227.243   442.1 2233.87   453.1 2236.68
   494.7 2236.99   533.2 2235.42   573.6 2240.14   588.2 2243.17   599.9 2249.14
   626.1 2265.28   646.6 2280.88     667 2294.29     719 2323.22   737.5 2336.91
   752.2 2341.36   763.4 2349.88   784.4 2362.44   813.1  2378.2   826.4 2384.32
#Mann= 4 ,-1 , 0
       0      .1       0  293.38      .1       0   407.7    .045       0
     432      .1       0
#XS Ineff= 2 , 0
          383.13  2230.6
Permanent Ineff=
       F       F
Bank Sta=407.7,432
XS Rating Curve= 0 ,0
Exp/Cntr=0.3,0.1

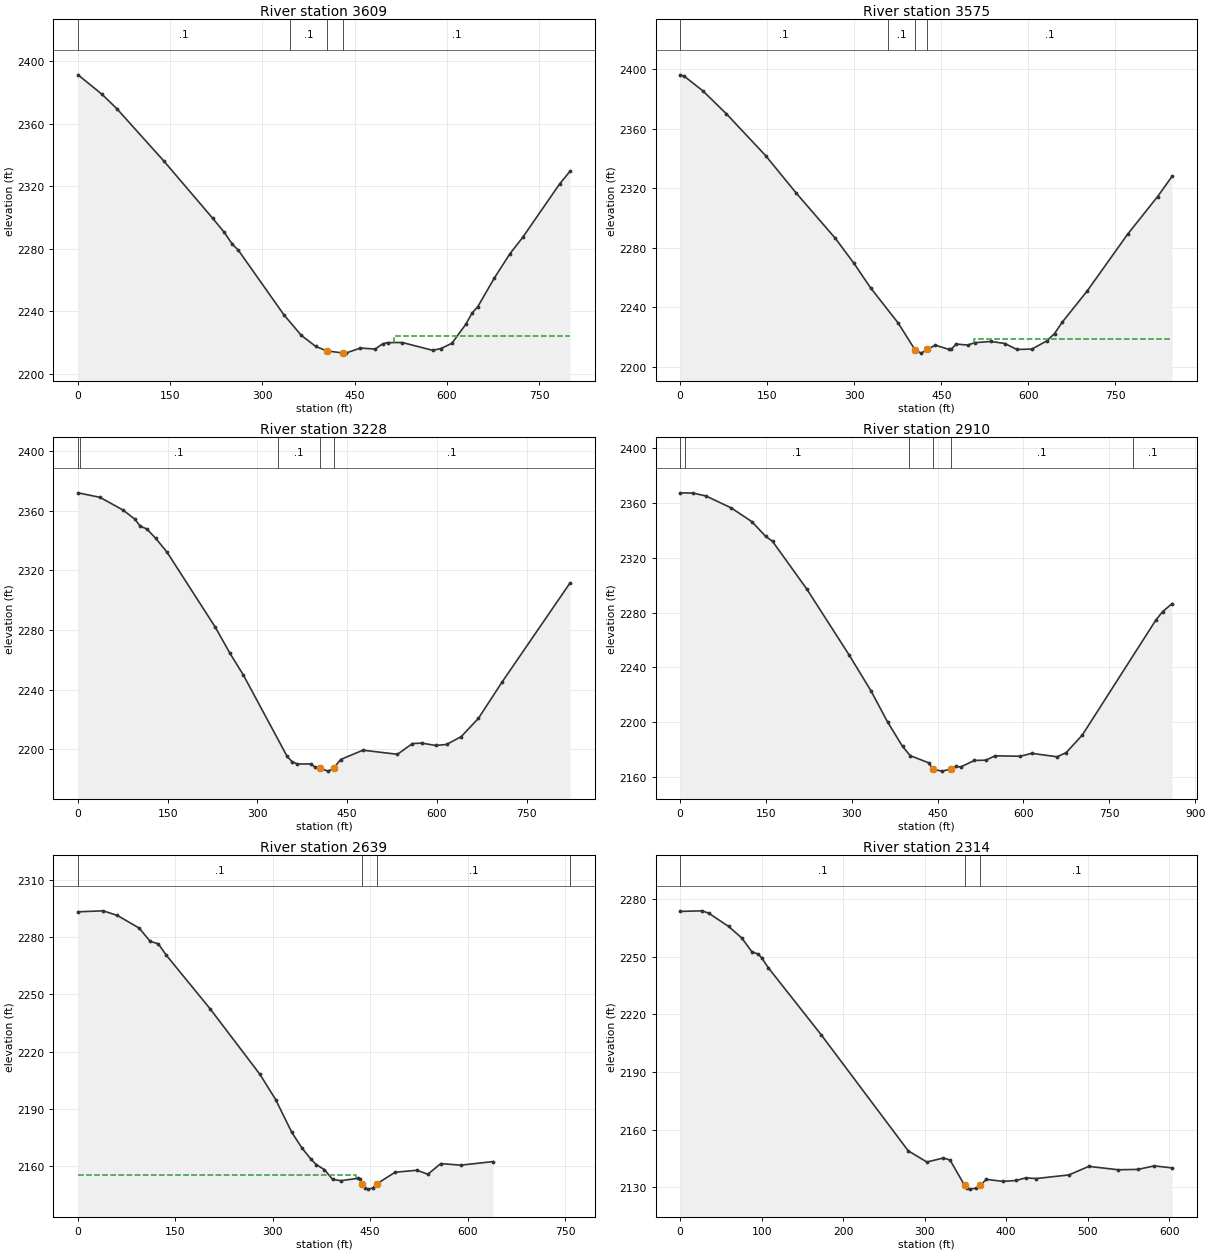
Type RM Length L Ch R = 1 ,3609    ,33.5,33.8,34.1
XS GIS Cut Line= 3
2398257.20626071 616313.797649832398231.19792848615785.271184194
 2398107.6583504615543.765242076
#Sta/Elev= 30
       0 2391.17      39 2378.73      63 2369.59   139.1 2336.32   219.2 2299.43
     238 2290.42   251.2 2282.81   260.9 2279.03   335.3 2237.57   363.3 2224.61
   386.8 2217.54   404.8 2214.71   431.4 2213.32   435.4 2213.27   459.3  2216.5
   483.5 2215.89   495.5 2219.22   503.5 2219.98   527.5 2220.06   576.8 2215.08
   590.2 2216.18   608.2 2219.55   630.7 2231.63   641.3 2239.02   650.2 2242.86
   676.9 2261.03   702.6 2276.79   723.4 2287.26   783.4 2321.38   800.4 2329.55
#Mann= 4 ,-1 , 0
       0      .1       0  345.38      .1       0   404.8    .045       0
   431.4      .1       0
#XS Ineff= 2 , 0
                          513.67         2223.99
Permanent Ineff=
       F       F
Bank Sta=404.8,431.4
XS Rating Curve= 0 ,0
Exp/Cntr(USF)=0,0
Exp/Cntr=0.3,0.1

Type RM Length L Ch R = 1 ,3575    ,347.9,347.2,339.7
XS GIS Cut Line= 3
2398273.33120962616322.3317762672398267.83050248615750.281676093
2398162.05030058615495.661608466
#Sta/Elev= 30
       0 2396.24     7.4 2395.21    39.4 2385.37    79.4 2370.12   147.4 2341.85
   200.1 2316.67   267.5 2286.22   299.5 2269.46     328 2253.05   375.5  2229.4
   404.8 2211.26   415.5 2209.06     426  2211.6   439.5 2214.41   463.5 2211.56
   467.5 2211.85   475.5 2215.17   495.5 2214.49   507.5 2216.07   535.5 2216.93
   559.5 2215.53   580.1 2211.52   606.1 2211.78   632.1 2217.35   645.1 2222.21
     658 2229.68     701 2250.67   771.3 2289.16   822.6 2314.31   847.8 2328.06
#Mann= 4 ,-1 , 0
       0      .1       0  358.12      .1       0   404.8    .045       0
     426      .1       0
#XS Ineff= 2 , 0
                          506.59         2218.85
Permanent Ineff=
       F       F
Bank Sta=404.8,426
XS Rating Curve= 0 ,0
Exp/Cntr=0.3,0.1

Type RM Length L Ch R = 1 ,3228    ,310.7,318.2,323.3
XS GIS Cut Line= 2
2398776.72609096616085.917391534     2398282.779      615428.206
#Sta/Elev= 30
       0 2371.95    36.6 2368.94      75 2360.47      95 2354.31   103.8 2349.67
     115  2347.7   129.9 2341.43   148.9  2332.1   229.3 2281.94   253.9 2264.39
   276.4 2249.73   349.7 2195.08   357.8 2191.66   366.4 2190.02     389 2190.08
   396.3 2187.93     404 2187.24   417.8 2185.26   427.2 2187.09     439 2193.05
   476.2 2199.31     534 2196.56   559.1 2203.77     575 2204.04   597.8 2202.47
   616.1 2203.15   640.7 2208.43   669.4  2220.7   709.2 2245.19   822.5 2311.49
#Mann= 5 ,-1 , 0
       0      .1       0    3.42      .1       0  335.03      .1       0
     404    .045       0   427.2      .1       0
Bank Sta=404,427.2
XS Rating Curve= 0 ,0
Exp/Cntr=0.3,0.1

Type RM Length L Ch R = 1 ,2910    ,273.2,270.7,268.7
XS GIS Cut Line= 2
 2398821.4970873 616083.84608186     2398759.601      615226.297
#Sta/Elev= 30
       0 2367.44    22.2 2367.27    45.1 2365.14    89.2 2356.44   125.3 2346.39
   149.3 2335.72   161.4 2332.02   221.5 2297.05   295.2 2249.07   333.8 2222.56
   362.5 2200.05   388.7 2182.18     402  2175.5   434.1 2170.27   442.1 2165.48
   458.1 2164.17   473.5 2165.79   482.2 2167.56   490.2 2167.21   514.3    2172
   534.3 2172.15   550.4 2175.36   594.5 2175.04   614.5 2177.17   658.7 2174.64
   674.7 2177.74   702.8 2190.52   831.1 2274.38   843.1 2280.65   859.8 2286.58
#Mann= 6 ,-1 , 0
       0      .1       0    7.87      .1       0  399.32      .1       0
   442.1    .045       0   473.5      .1       0  790.76      .1       0
Bank Sta=442.1,473.5
XS Rating Curve= 0 ,0
Exp/Cntr=0.3,0.1

Type RM Length L Ch R = 1 ,2639    ,319.8,325.1,328.3
XS GIS Cut Line= 2
2399153.48641066 615992.787169162398961.73437222615383.079554616
#Sta/Elev= 30
       0 2293.31    38.8 2293.82    60.7 2291.38    94.2 2284.78     111 2277.86
   123.6 2276.55   136.2 2270.48   203.3 2242.56   280.1  2208.2   304.6 2194.81
   329.1 2177.83     345 2169.55   358.4 2163.85   366.8 2160.93   379.4 2158.26
     392 2153.22   404.5 2152.47   431.1 2153.74   433.9 2153.46     438 2150.93
   442.3 2148.49   446.5 2148.06   453.5 2148.57   459.9 2150.79   488.4 2156.92
   521.9 2157.93   538.7 2155.86   558.7 2161.44     589 2160.61   639.1 2162.48
#Mann= 4 ,-1 , 0
       0      .1       0     438    .045       0   459.9      .1       0
  757.63      .1       0
#XS Ineff= 2 , 0
          428.74 2155.68
Permanent Ineff=
       F       F
Bank Sta=438,459.9
XS Rating Curve= 0 ,0
Exp/Cntr=0.3,0.1

Type RM Length L Ch R = 1 ,2314    ,287,285.3,280.1
XS GIS Cut Line= 3
 2399236.2962619616005.6407822042399317.48324694615507.563511562
2399308.22058785615409.087382434
#Sta/Elev= 30
       0 2273.47    27.1 2273.77    35.2  2272.5    59.5 2265.65    75.7 2259.61
    87.9 2252.53      96 2251.24   100.1 2249.26   108.2 2244.17     173 2209.37
   279.8 2149.05   302.7 2143.24     323 2145.34   331.1 2144.27     349 2131.08
   351.3  2129.8   355.4 2129.15   363.5 2129.65   368.4 2131.25   375.6 2134.25
   395.9 2133.17   412.1 2133.64   424.3 2135.03   436.6 2134.65     477 2136.53
   501.3 2140.98   537.5 2139.21   561.6 2139.41   581.7 2141.22   603.6 2140.18
#Mann= 3 ,-1 , 0
       0      .1       0     349    .045       0   368.4      .1       0
Bank Sta=349,368.4
XS Rating Curve= 0 ,0
Exp/Cntr=0.3,0.1

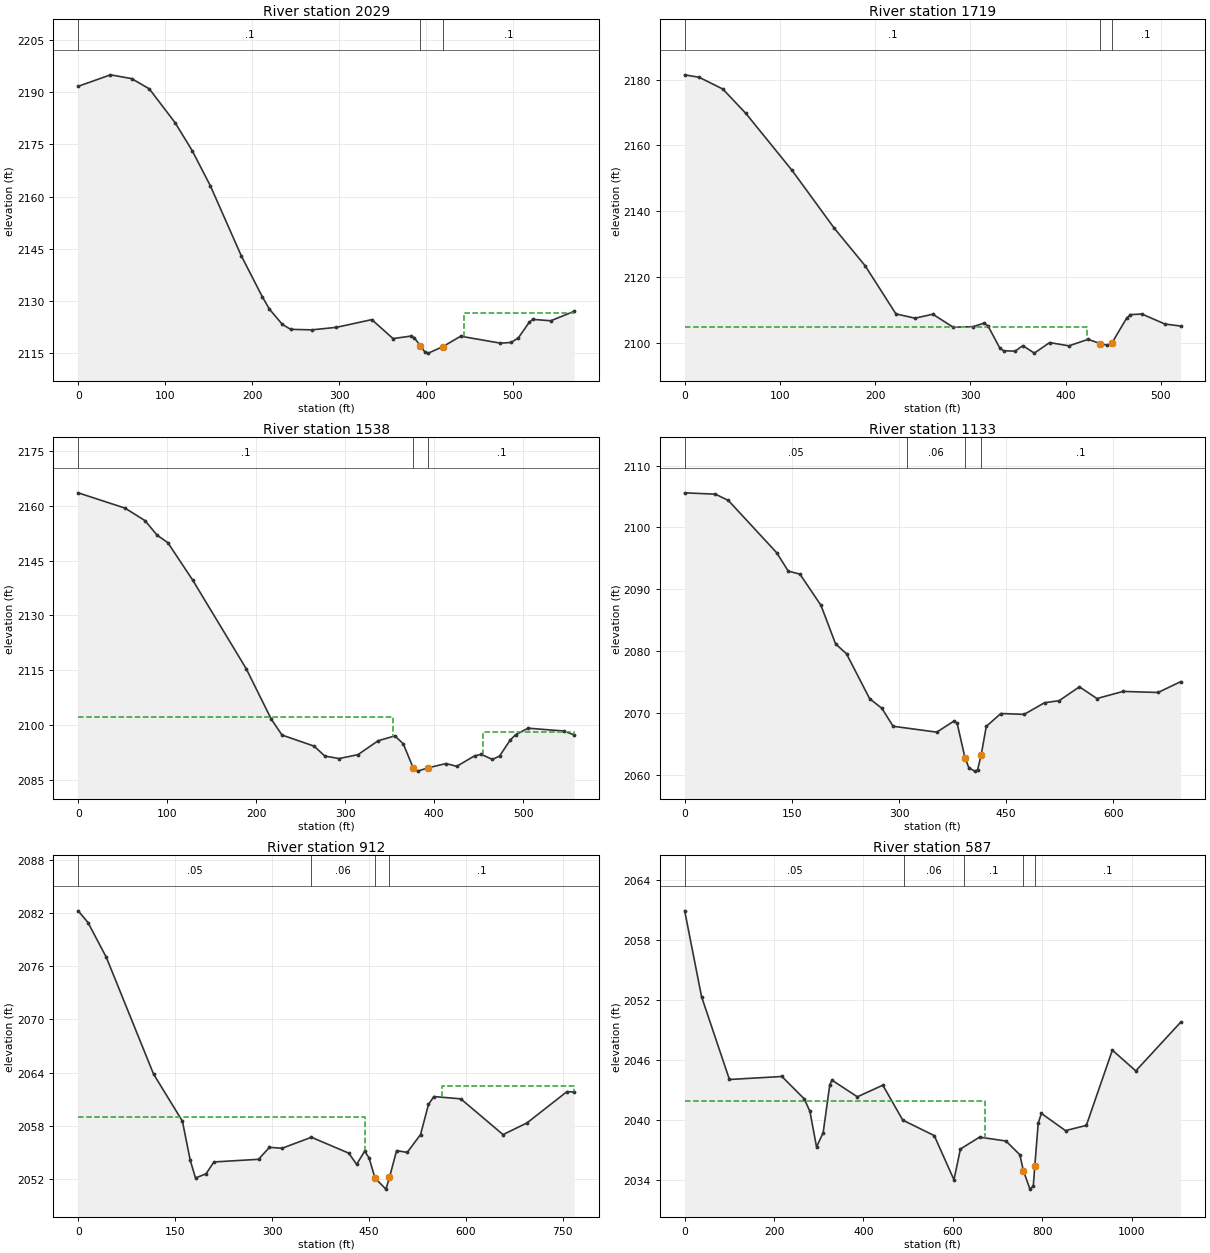
Type RM Length L Ch R = 1 ,2029    ,306.2,309.2,310.7
XS GIS Cut Line= 3
     2399622.135      615979.449     2399551.788      615581.027
2399508.61964825615420.976676985
#Sta/Elev= 30
       0 2191.69    37.1 2194.99    61.5  2193.9    81.8 2190.95   111.5 2181.21
   131.1  2173.2   151.9 2163.14   187.4 2143.06   211.8 2131.17   219.9 2127.66
   234.7 2123.28   244.3 2121.84   268.7 2121.69   296.9 2122.41   337.7 2124.63
   362.1 2119.18   382.4 2119.89   386.4 2119.47   393.5 2117.13   398.6 2115.38
   402.7    2115   419.2 2116.84   439.9 2119.86   485.5 2117.87   497.9 2118.06
   506.2 2119.37   518.7 2123.85   522.8  2124.7   543.5  2124.3   570.4 2127.01
#Mann= 3 ,-1 , 0
       0      .1       0   393.5    .045       0   419.2      .1       0
#XS Ineff= 2 , 0
                          443.53         2126.53
Permanent Ineff=
       F       F
Bank Sta=393.5,419.2
XS Rating Curve= 0 ,0
Exp/Cntr=0.3,0.1

Type RM Length L Ch R = 1 ,1719    ,181.4,181.4,177.9
XS GIS Cut Line= 2
     2399765.448      615954.6462399835.23503499615438.623081495
#Sta/Elev= 30
       0 2181.48    15.2 2180.73    40.1 2177.15    64.3 2169.73   112.8 2152.41
   156.9 2134.92   189.5 2123.43   221.8  2108.8   241.9  2107.5   260.5 2108.71
   281.8 2104.78   302.5  2104.9   314.6 2106.02   318.6 2105.09   330.7  2098.5
   334.8 2097.61   346.9 2097.48     355 2099.16   367.1 2096.88   383.2 2100.09
   403.4 2099.09   423.6 2101.07   436.22099.792   443.8 2099.27   448.42099.885
   463.9 2107.45     468 2108.59   480.1 2108.76   504.3 2105.72   520.7 2105.12
#Mann= 3 ,-1 , 0
       0      .1       0   436.2    .045       0   448.4      .1       0
#XS Ineff= 2 , 0
          422.29 2104.72
Permanent Ineff=
       F       F
Bank Sta=436.2,448.4
XS Rating Curve= 0 ,0
Exp/Cntr=0.3,0.1

Type RM Length L Ch R = 1 ,1538    ,408.4,404.7,400.5
XS GIS Cut Line= 2
 2399958.0967191 615979.421671912399992.64589296 615423.25956072
#Sta/Elev= 30
       0 2163.52    52.6 2159.34      75 2155.93    88.7 2151.93   100.7 2149.89
   128.8 2139.58   188.9 2115.36   216.9 2101.63     229 2097.28     265 2094.25
   277.1 2091.53   293.1 2090.85   314.3 2091.91   336.9 2095.71   355.8 2097.05
   365.2 2094.88   376.3 2088.33   381.3 2087.41   393.42088.335   413.3 2089.48
   425.3 2088.72   445.4  2091.6   452.8    2092   465.4  2090.6   473.4 2091.54
   485.5 2095.95   491.6 2097.41   505.5 2099.15   545.6 2098.38   557.2 2097.32
#Mann= 3 ,-1 , 0
       0      .1       0   376.3    .045       0   393.4      .1       0
#XS Ineff= 2 , 0
           353.2 2102.26  454.66         2098.18
Permanent Ineff=
       F       F
Bank Sta=376.3,393.4
XS Rating Curve= 0 ,0
Exp/Cntr=0.3,0.1

Type RM Length L Ch R = 1 ,1133    ,221.4,221.2,220.6
XS GIS Cut Line= 2
     2400440.119      615941.2062400307.26700148615259.969825548
#Sta/Elev= 30
       0  2105.6    43.1 2105.38    61.1 2104.37   128.7 2095.93     145 2092.95
   161.3 2092.46   190.7 2087.43   211.2 2081.19   226.5 2079.59   258.9 2072.33
     276 2070.78   291.7 2067.88   352.8 2066.93   377.3 2068.75   381.4 2068.33
   392.32062.795   397.7 2061.19   405.8 2060.63   409.9 2060.82     4152063.257
   422.1 2067.86   442.5 2069.94   475.1  2069.8   503.6 2071.68     524 2072.01
   552.5 2074.25     577 2072.36   613.6 2073.51   662.6 2073.34   694.1 2075.08
#Mann= 4 ,-1 , 0
       0     .05       0  310.74     .06       0   392.3    .045       0
     415      .1       0
Bank Sta=392.3,415
XS Rating Curve= 0 ,0
Exp/Cntr=0.3,0.1

Type RM Length L Ch R = 1 ,912     ,330.3,325.1,318.7
XS GIS Cut Line= 3
2400558.19440187615953.7101698212400613.62741509615642.878890588
2400505.19354439615204.004389278
#Sta/Elev= 30
       0 2082.27    15.1 2080.95    43.5 2077.02   116.7 2063.82   161.3 2058.51
   173.5 2054.07   181.6 2052.09   197.9 2052.56   210.1  2053.9   279.2  2054.2
     296 2055.55   315.7 2055.45     361 2056.69   418.7  2054.9   431.1 2053.63
   443.5 2055.12   450.3 2054.35   459.5 2052.08   476.4 2050.83   481.92052.158
   492.9 2055.18   509.4 2054.98     530    2057   542.3  2060.4   550.6 2061.29
   592.3 2061.03   657.7 2056.99   694.8 2058.31   756.6 2061.84   767.8 2061.81
#Mann= 4 ,-1 , 0
       0     .05       0     361     .06       0   459.5    .045       0
   481.9      .1       0
#XS Ineff= 2 , 0
       0   443.5 2058.95  563.67       0 2062.45
Permanent Ineff=
       F       F
Bank Sta=459.5,481.9
XS Rating Curve= 0 ,0
Exp/Cntr=0.3,0.1

Type RM Length L Ch R = 1 ,587     ,297.8,307.8,314.4
XS GIS Cut Line= 3
2400605.47934869615953.4753361092400959.70435702615466.197237844
2400591.18921475615118.008718912
#Sta/Elev= 30
       0 2060.89    37.8  2052.3   100.1 2044.03   217.5 2044.33   267.5 2042.09
   280.1 2040.85     295 2037.28   309.8 2038.72   324.6 2043.51   329.6 2043.96
   386.3  2042.3   443.3 2043.46   487.8 2039.97   558.3 2038.42   602.4    2034
   616.8 2037.08   659.7 2038.27   718.6 2037.88   749.7 2036.51   757.8  2034.9
   772.4 2033.07   779.8 2033.37   783.22035.372   790.8 2039.65   797.9 2040.64
   851.9 2038.92   898.5 2039.44   956.7 2046.96  1009.1 2044.89  1109.4 2049.75
#Mann= 5 ,-1 , 0
       0     .05       0  490.92     .06       0  625.73      .1       0
   757.8    .045       0   783.2      .1       0
#XS Ineff= 2 , 0
          671.25 2041.91
Permanent Ineff=
       F       F
Bank Sta=757.8,783.2
XS Rating Curve= 0 ,0
Exp/Cntr=0.3,0.1