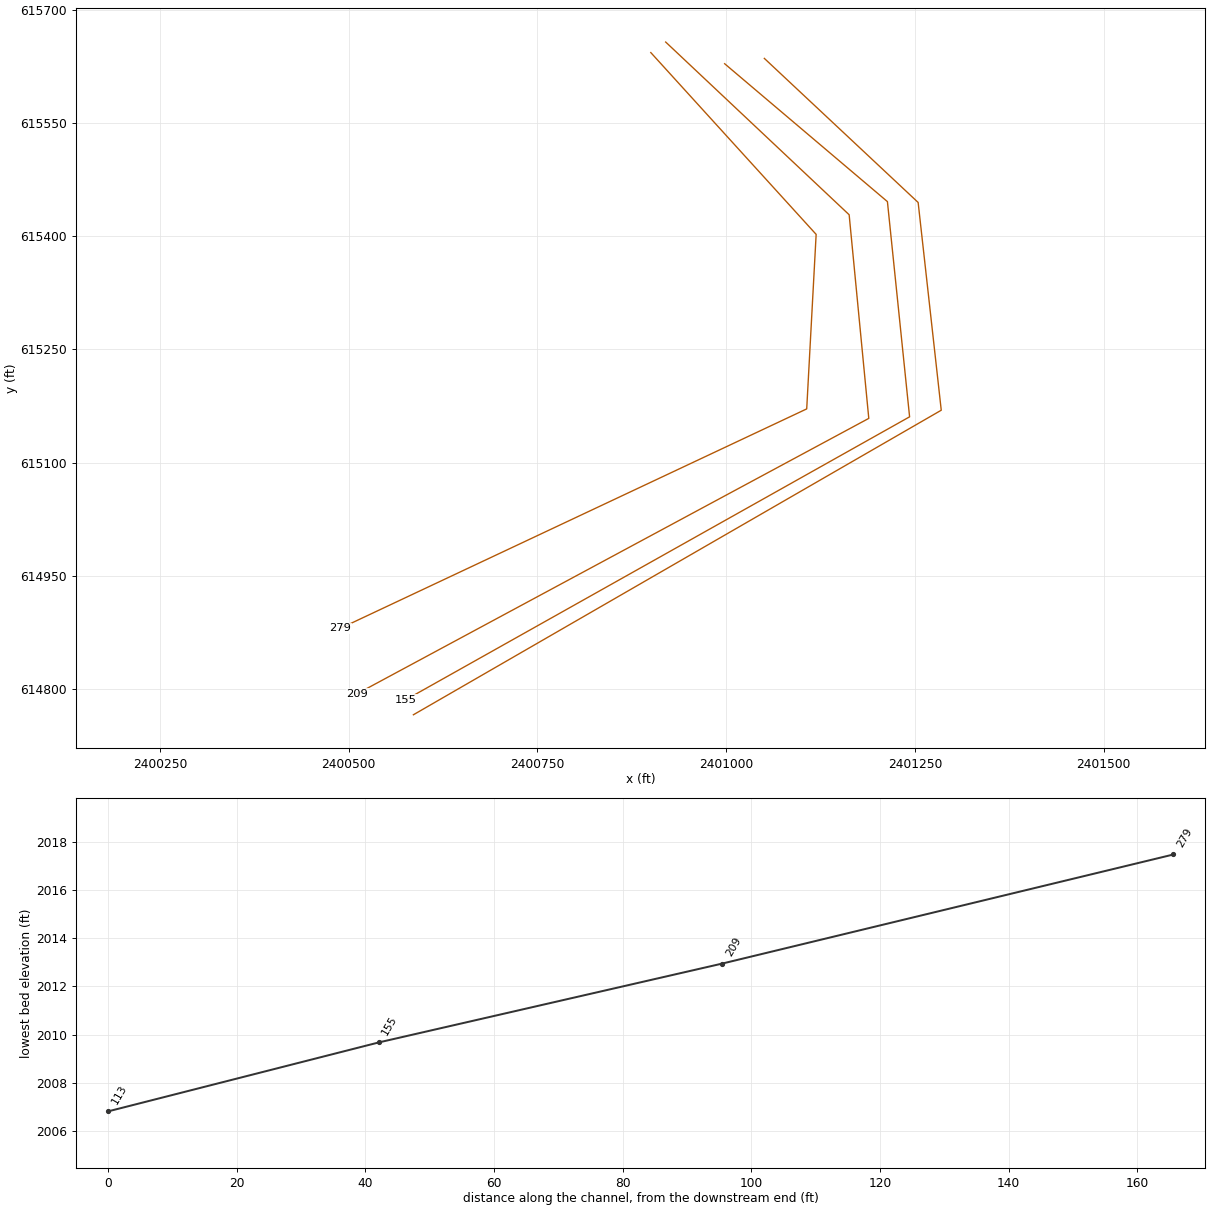
HEC-RAS study REDLCKRN.prj: REDLCKRN

--- REDLCKRN.g01 (geometry) --- (continued)

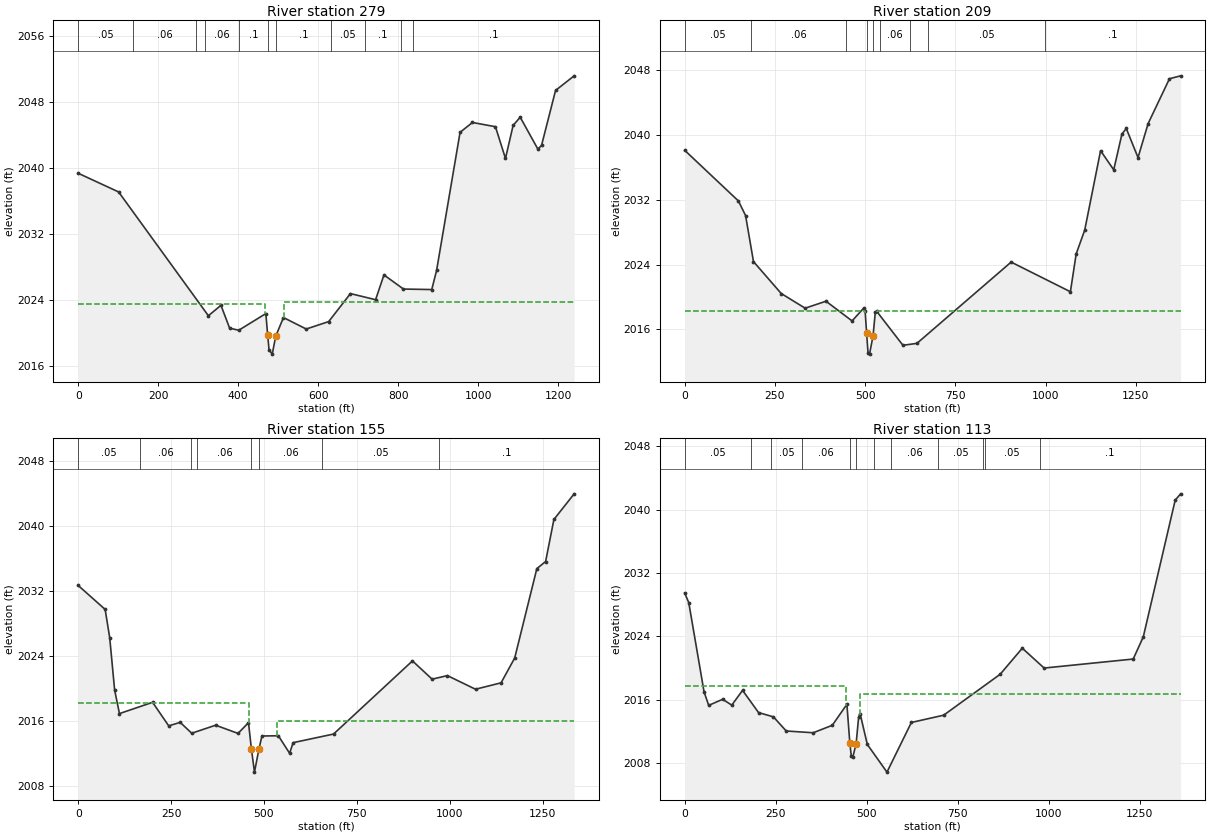
Type RM Length L Ch R = 1 ,279     ,68.6,70.1,71.5
XS GIS Cut Line= 4
2400900.23325724615643.0616951632401119.21299558615402.339387283
2401106.71883603615171.2435089312400488.67996889614880.532144509
#Sta/Elev= 30
       0 2039.37     101 2037.11   325.4 2022.12   356.9 2023.38   378.5 2020.62
   401.3 2020.36   469.1 2022.38   473.6 2019.81   477.1    2018   485.1 2017.47
   493.7 2019.62   513.1  2021.9   570.1 2020.51   626.2 2021.41   680.6  2024.8
   743.5 2024.06   764.4 2027.06   813.2 2025.35   883.9 2025.29     896 2027.61
   954.7 2044.33   985.6 2045.52  1043.1 2045.01  1068.2 2041.16  1087.3 2045.16
    1105 2046.16  1149.3 2042.29  1158.4 2042.75  1193.4  2049.4  1239.9 2051.17
#Mann= 11 ,-1 , 0
       0     .05       0  137.96     .06       0  293.36      .1       0
  315.89     .06       0  403.22      .1       0   473.6    .045       0
   493.7      .1       0  632.26     .05       0  716.15      .1       0
  806.57     .05       0  836.52      .1       0
#XS Ineff= 2 , 0
          466.85 2023.54  514.16         2023.76
Permanent Ineff=
       F       F
Bank Sta=473.6,493.7
XS Rating Curve= 0 ,0
Exp/Cntr=0.5,0.3

Type RM Length L Ch R = 1 ,209     ,53.3,53.4,53.6
XS GIS Cut Line= 4
2400919.93147192615657.0235062492401162.92935543615428.326425973
2401188.93199805615158.6925921242400511.54708394614794.252785822
#Sta/Elev= 30
       0 2038.11     149 2031.85   168.7 2030.05   190.6 2024.37   267.5 2020.43
   333.7 2018.62   391.4 2019.48   463.7 2017.05   495.9 2018.63   499.9 2018.24
     5042015.543   507.9 2013.09     512 2012.95   521.8  2015.2     528 2018.09
     532 2018.23   604.6 2014.04   643.4 2014.28   904.3 2024.31  1068.5 2020.65
  1084.5 2025.32  1108.1 2028.25  1152.1 2038.06  1188.5  2035.7  1211.2 2040.11
  1223.3  2040.8  1255.8 2037.21  1283.8 2041.41  1342.9 2046.94  1373.8  2047.3
#Mann= 9 ,-1 , 0
       0     .05       0  182.89     .06       0  447.02      .1       0
     504    .045       0   521.8      .1       0  541.76     .06       0
  624.69      .1       0  674.87     .05       0  998.14      .1       0
#XS Ineff= 2 , 0
          500.28 2018.24  532.95         2018.22
Permanent Ineff=
       F       F
Bank Sta=504,521.8
XS Rating Curve= 0 ,0
Exp/Cntr=0.5,0.3

Type RM Length L Ch R = 1 ,155     ,42.1,42.1,42.6
XS GIS Cut Line= 4
2400998.01948054615628.3139913732401213.61072844615445.724755289
2401242.98610907615160.7614110052400575.18102068 614785.84407057
#Sta/Elev= 30
       0 2032.67    72.5 2029.72    84.8 2026.23      98  2019.8     111 2016.89
   200.2 2018.28   243.6 2015.38   274.5 2015.81   305.5 2014.47   369.8 2015.46
   430.1 2014.45   458.3 2015.77   466.3 2012.47   474.4 2009.68   486.4 2012.52
   494.5 2014.13   538.7 2014.16     569    2012   578.4 2013.31   687.2 2014.37
   899.6 2023.38   952.5 2021.13   993.6 2021.57  1069.3 2019.89  1138.1 2020.68
  1174.8 2023.74  1234.4 2034.75    1258 2035.62  1280.3  2040.8  1334.8 2043.96
#Mann= 8 ,-1 , 0
       0     .05       0   166.9     .06       0  304.11     .05       0
  321.03     .06       0   466.3    .045       0   486.4     .06       0
  657.17     .05       0  970.24      .1       0
#XS Ineff= 2 , 0
          459.41 2018.14  536.14         2015.93
Permanent Ineff=
       F       F
Bank Sta=466.3,486.4
XS Rating Curve= 0 ,0
Exp/Cntr(USF)=0,0
Exp/Cntr=0.5,0.3

Type RM Length L Ch R = 1 ,113     ,,,
XS GIS Cut Line= 4
 2401050.6046718 615635.355864762401254.30677483615444.599152673
2401284.91450077 615169.496492612400585.80464702614766.240495577
#Sta/Elev= 30
       0 2029.46    11.2 2028.26    53.3 2016.96      66 2015.26   104.3 2016.03
   129.4 2015.29   159.1 2017.16     203 2014.35   243.8 2013.81   279.1 2012.02
   353.2  2011.8   405.6 2012.74   445.8 2015.39   453.9 2010.49   457.9 2008.84
   461.9 2008.69   471.12010.403     478 2013.75     482 2014.23   501.9 2010.32
   555.9 2006.82     623  2013.1   711.7 2014.02   866.9 2019.19   927.8 2022.49
   987.8 2019.98  1232.6 2021.12  1260.3 2023.92    1348 2041.21  1362.9 2042.01
#Mann= 12 ,-1 , 0
       0     .05       0  181.17     .06       0  237.23     .05       0
  322.99     .06       0   453.9    .045       0   471.1     .06       0
  519.87     .05       0  568.34     .06       0  696.48     .05       0
  819.72     .06       0  824.61     .05       0  975.34      .1       0
#XS Ineff= 2 , 0
          442.78 2017.69  483.12         2016.65
Permanent Ineff=
       F       F
Bank Sta=453.9,471.1
XS Rating Curve= 0 ,0
Exp/Cntr(USF)=0,0
Exp/Cntr=0.3,0.1
LCMann Table=0

Chan Stop Cuts=-1
Use User Specified Reach Order=0
Composite Channel Slope=5